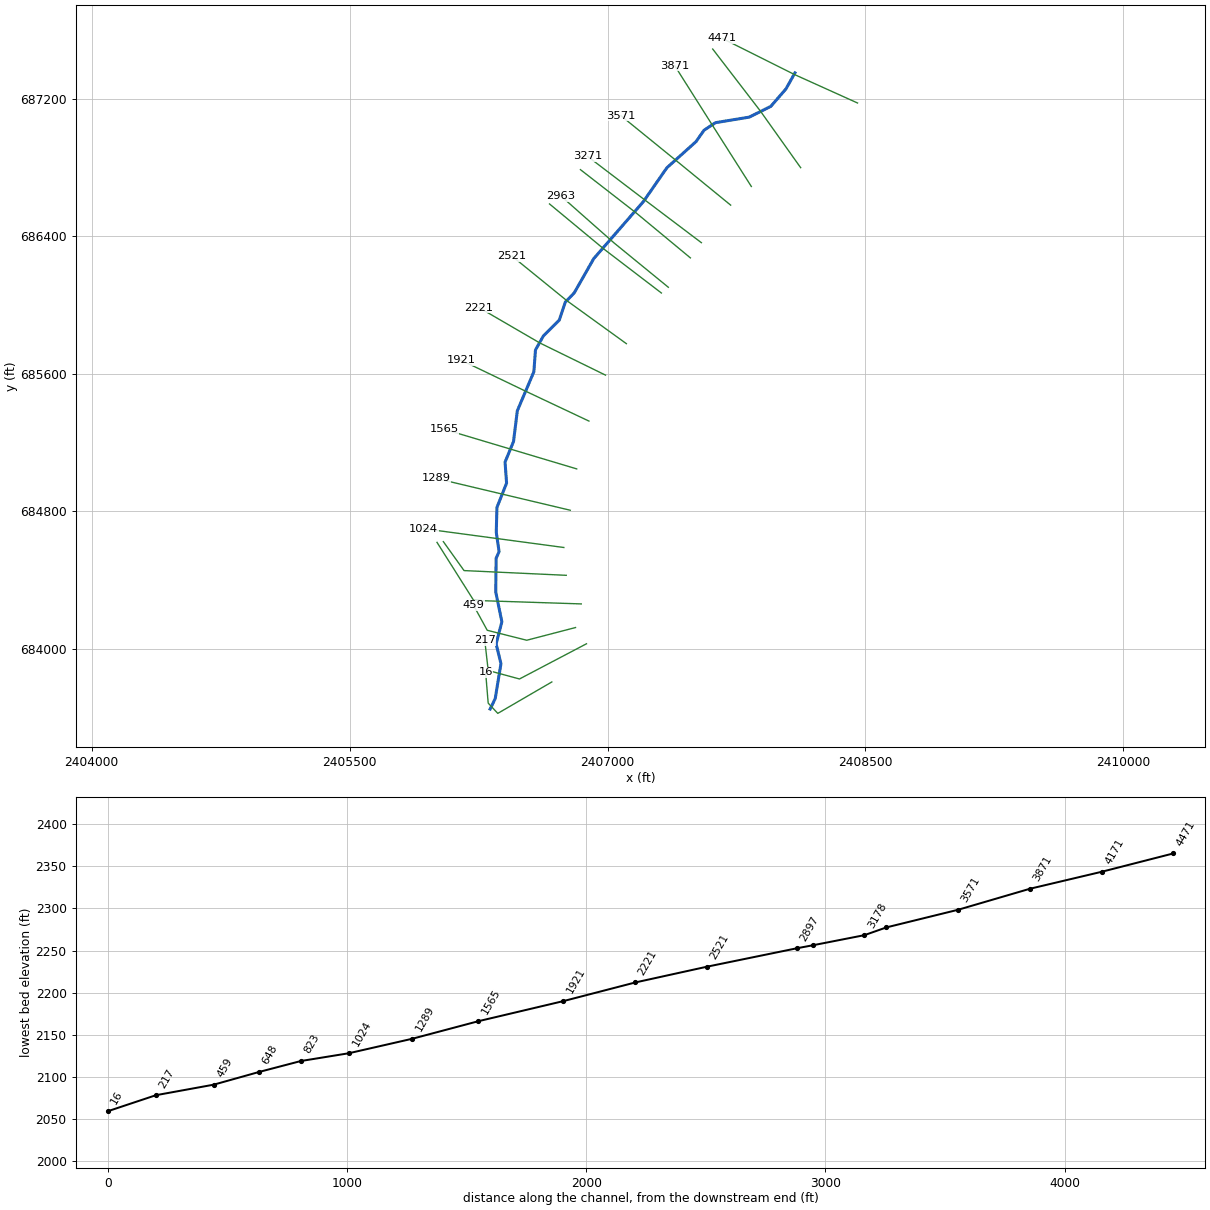
--- MCINTSHRN.prj (project) ---

Proj Title=MCINTSHRN
Current Plan=p01
Default Exp/Contr=0,0
English Units
Geom File=g01
Flow File=f01
Plan File=p01
BEGIN DESCRIPTION:
Stream Name: McIntosh Run
Flood Zone: Approximate
Pendleton County, West Virginia
HEC-RAS Version: 5.0.7
Hydrology Method:
Regression equation
END DESCRIPTION:
DSS Export Rating Curves= 0
DSS Export Rating Curve Sorted= 0
DSS Export Volume Flow Curves= 0
DXF OffsetX= 0
DXF OffsetY= 0
DXF ScaleX= 0
DXF ScaleY= 0

--- MCINTSHRN.p01 (plan) ---

Plan Title=Floodplain
Program Version=5.07
Short Identifier=Floodplain
Geom File=g01
Flow File=f01
Subcritical Flow
K Sum by GR= 0
Std Step Tol= 0.01
Critical Tol= 0.01
Num of Std Step Trials= 20
Max Error Tol= 0.3
Flow Tol Ratio= 0.001
Split Flow NTrial= 30
Split Flow Tol= 0.02
Split Flow Ratio= 0.02
Log Output Level= 0
Friction Slope Method= 1
Unsteady Friction Slope Method= 2
Unsteady Bridges Friction Slope Method= 1
Parabolic Critical Depth
Global Vel Dist= 0 , 0 , 0
Global Log Level= 0
CheckData=True
Encroach Param=-1 ,0,0, 0
Mapping Interval=1HOUR
Computation Time Step Use Courant=        0
Computation Time Step Use Time Series=    0
Computation Time Step Count To Double=0
Computation Time Step Max Doubling=0
Computation Time Step Max Halving=0
Computation Time Step Residence Courant=0
Run HTab= 0
Run UNet= 0
Run Sediment= 0
Run PostProcess= 0
Run WQNet= 0
Run RASMapper= 0
UNET Theta= 0
UNET Theta Warmup= 0
UNET ZTol= 0
UNET ZSATol= 0
UNET MxIter= 0
UNET Max Iter WO Improvement= 0
UNET MaxInSteps= 0
UNET DtIC= 0
UNET DtMin= 0
UNET MaxCRTS= 0
UNET WFStab= 0
UNET SFStab= 0
UNET WFX= 1
UNET SFX= 1
UNET 1D Methodology=Finite Difference
UNET DSS MLevel= 1
UNET Pardiso=0
UNET DZMax Abort= 0
UNET Use Existing IB Tables= 0
UNET Froude Reduction=False
UNET Froude Limit= 0
UNET Froude Power= 0
UNET D1 Cores= 0
UNET D2 Coriolis=0
UNET D2 Cores= 0
UNET D2 Theta= 1
UNET D2 Theta Warmup= 1
UNET D2 Z Tol= 0.01
UNET D2 Volume Tol= 0.01
UNET D2 Max Iterations= 20
UNET D2 Equation= 0
UNET D2 RampUpFraction=0.1
UNET D2 TimeSlices= 1
UNET D2 BCVolumeCheck=0
UNET D1D2 MaxIter= 0
UNET D1D2 ZTol=0.01
UNET D1D2 QTol=0.1
UNET D1D2 MinQTol=1
Write IC File= 0
Write IC File at Fixed DateTime=0
Write IC File at Sim End=0
Echo Input=False
Echo Parameters=False
Echo Output=False
Write Detailed= 0
HDF Write Warmup=0
HDF Write Time Slices=0
HDF Flush=0
HDF Face Node Velocities=0
HDF Compression= 1
HDF Chunk Size= 1
HDF Spatial Parts= 1
HDF Use Max Rows=0
HDF Fixed Rows= 1
Calibration Method= 0
Calibration Iterations= 20
Calibration Max Change=0.05
Calibration Tolerance=0.2
Calibration Maximum=1.5
Calibration Minimum=0.5
Calibration Optimization Method= 1
WQ AD Non Conservative
WQ ULTIMATE=-1
WQ Max Comp Step=1HOUR
WQ Output Interval=15MIN
WQ Output Selected Increments= 0
WQ Output face flow=0
WQ Output face velocity=0
WQ Output face area=0
WQ Output face dispersion=0
WQ Output cell volume=0
WQ Output cell surface area=0
WQ Output cell continuity=0
WQ Output cumulative cell continuity=0
WQ Output face conc=0
WQ Output face dconc_dx=0
WQ Output face courant=0
WQ Output face peclet=0
WQ Output face adv mass=0
WQ Output face disp mass=0
WQ Output cell mass=0
WQ Output cell source sink temp=0
WQ Output nsm pathways=0
WQ Output nsm derived pathways=0
WQ Output MaxMinRange=-1
WQ Daily Max Min Mean=-1
WQ Daily Range=0
WQ Daily Time=0
WQ Create Restart=0
WQ Fixed Restart=0
WQ System Summary=0
WQ Write To DSS=0
WQ Use Fixed Temperature=0
Sorting and Armoring Iterations= 10
XS Update Threshold= 0.02
Bed Roughness Predictor= 0
Hydraulics Update Threshold= 0.02
Energy Slope Method= 1
Volume Change Method= 1
Sediment Retention Method= 0
XS Weighting Method= 0
Number of US Weighted Cross Sections= 1
Number of DS Weighted Cross Sections= 1
Upstream XS Weight=0
Main XS Weight=1
Downstream XS Weight=0
Number of DS XS's Weighted with US Boundary= 1
Upstream Boundary Weight= 1
Weight of XSs Associated with US Boundary= 0
Number of US XS's Weighted with DS Boundary= 1
Downstream Boundary Weight= 0.5
Weight of XSs Associated with DS Boundary= 0.5
Percentile Method= 0
Sediment Output Level= 3
Mass or Volume Output= 0
Output Increment Type= 1
Profile and TS Output Increment= 1
XS Output Flag= 0
XS Output Increment= 10
Write Gradation File= 0
Read Gradation Hotstart= 0
Write HDF5 File= 1
Write Binary Output= 1
Write DSS Sediment File= 0
SV Curve= 0
Specific Gage Flag= 0

--- MCINTSHRN.f01 (steady flow) ---

Flow Title=Flows
Program Version=5.07
Number of Profiles= 6
Profile Names=P100yr,P10yr,P25yr,P50yr,P500yr,P101yr
River Rch & RM=MCINTSHRN,Main            ,4471
     588     275     389     486     863     716
River Rch & RM=MCINTSHRN,Main            ,2521
     659     307     435     543     967     802
Boundary for River Rch & Prof#=MCINTSHRN,Main            , 1
Up Type= 0
Dn Type= 3
Dn Slope=0.0957
Boundary for River Rch & Prof#=MCINTSHRN,Main            , 2
Up Type= 0
Dn Type= 3
Dn Slope=0.0957
Boundary for River Rch & Prof#=MCINTSHRN,Main            , 3
Up Type= 0
Dn Type= 3
Dn Slope=0.0957
Boundary for River Rch & Prof#=MCINTSHRN,Main            , 4
Up Type= 0
Dn Type= 3
Dn Slope=0.0957
Boundary for River Rch & Prof#=MCINTSHRN,Main            , 5
Up Type= 0
Dn Type= 3
Dn Slope=0.0957
Boundary for River Rch & Prof#=MCINTSHRN,Main            , 6
Up Type= 0
Dn Type= 3
Dn Slope=0.0957
DSS Import GetInterval= 0
DSS Import GetPeak= 0
DSS Import FillOption= 0

--- MCINTSHRN.g01 (geometry) ---

Geom Title=Geometry
Program Version=5.07

River Reach=MCINTSHRN       ,Main
Reach XY= 30
     2408089.909      687349.497     2408037.726      687256.639
     2407949.621      687154.867     2407824.301      687092.323
     2407627.942      687059.979     2407561.285      687016.154
       2407514.7      686949.938     2407344.911      686797.433
     2407208.471      686600.893     2406919.385      686268.821
     2406806.437      686070.232     2406754.448      686016.371
     2406719.452      685911.634     2406627.361      685820.451
     2406581.035      685738.301     2406571.778      685611.691
     2406475.506      685384.633     2406453.425         685206.
     2406404.248      685086.516     2406413.088      684964.044
     2406357.001      684822.853     2406353.057      684678.283
     2406369.555      684565.848     2406352.272      684526.993
     2406350.113      684330.987     2406385.734      684158.029
     2406352.293      684028.668     2406380.436      683914.342
     2406347.069      683711.427     2406317.542       683650.46

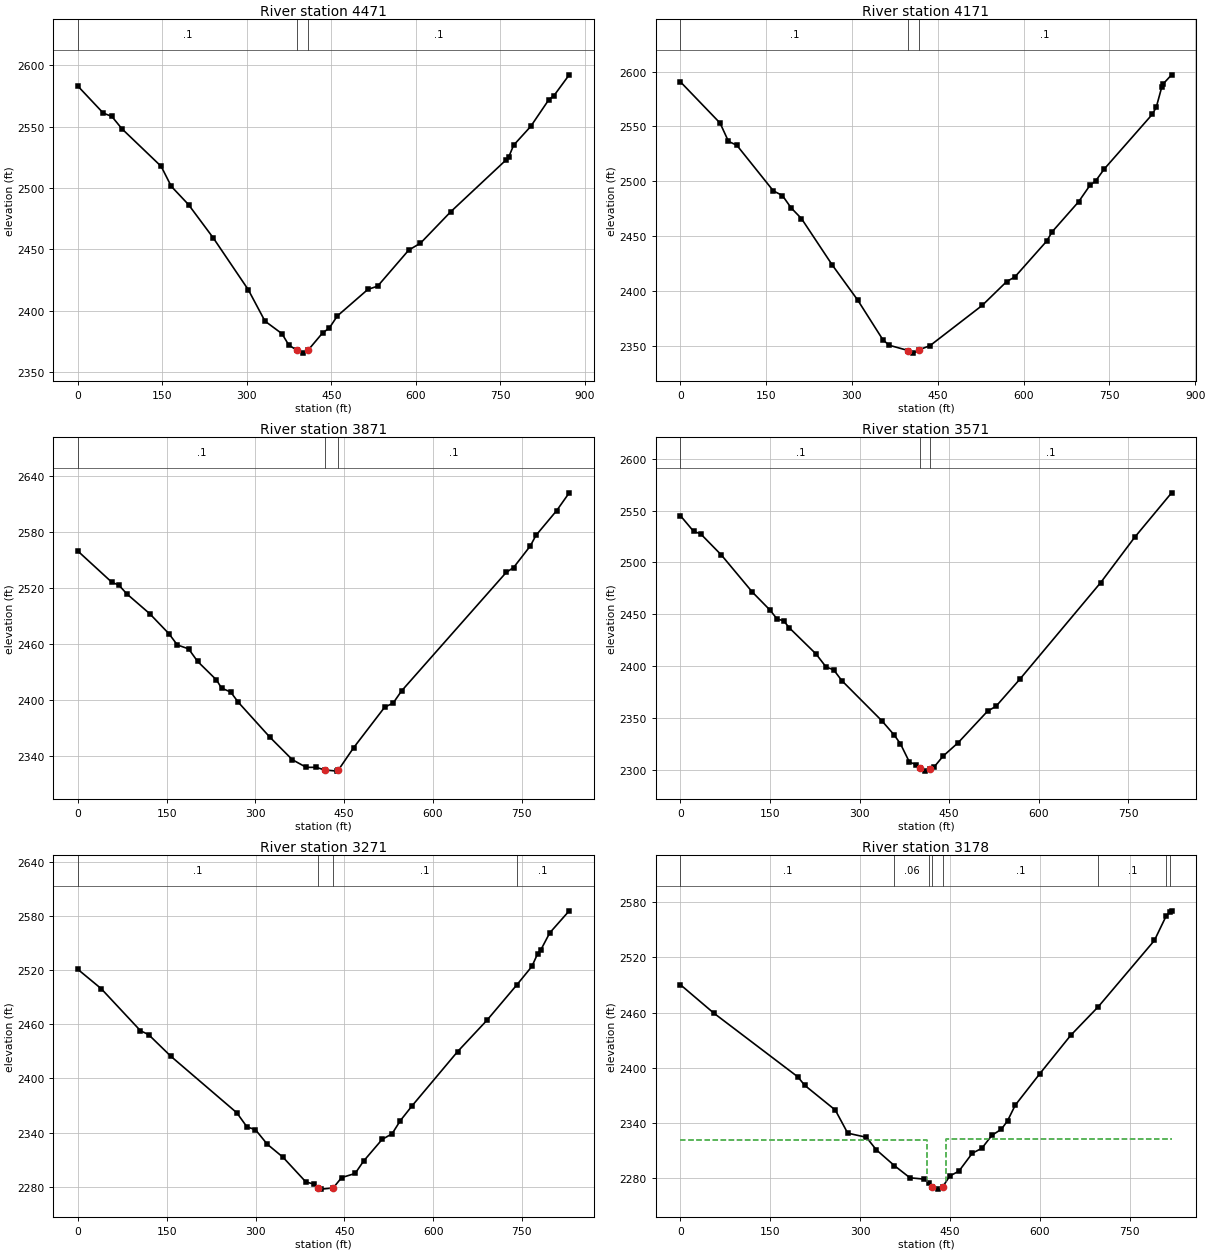
Type RM Length L Ch R = 1 ,4471    ,307.3,300,293.5
XS GIS Cut Line= 3
2408453.74367353687174.416248514     2408087.234      687339.921
     2407666.352      687550.422
#Sta/Elev= 30
       0 2582.86      45 2560.96    60.1 2558.29    78.2 2548.15   147.8 2517.61
   165.7 2501.38   196.4 2486.45   240.3 2459.37   302.5 2417.19   332.2 2391.59
   362.4 2381.36   374.5 2372.12   389.5 2367.74   399.6 2365.53   408.8 2367.94
   434.5 2381.95   446.5 2385.97   460.8 2395.82     515 2417.42   532.4 2420.08
   587.6 2449.44   608.4 2455.04   662.1 2480.61   760.5 2522.84   765.5  2525.5
   773.9 2534.83   804.2 2550.09   836.5 2571.91   845.5 2575.15   872.7 2592.15
#Mann= 3 ,-1 , 0
       0      .1       0   389.5    .045       0   408.8      .1       0
Bank Sta=389.5,408.8
XS Rating Curve= 0 ,0
Exp/Cntr=0.3,0.1

Type RM Length L Ch R = 1 ,4171    ,299.9,300,298.5
XS GIS Cut Line= 3
2408123.01266195686798.357399322     2407888.127      687128.587
     2407611.708      687488.124
#Sta/Elev= 30
       0 2590.72    69.4 2553.14    84.1 2536.48    98.8 2532.88   162.6 2491.36
   178.4 2487.16   193.7 2475.88   211.7 2466.19   265.7 2423.81   309.9 2392.08
   354.1 2355.83   364.9 2350.88   398.3 2346.03   407.5 2343.67   416.4 2346.55
   436.4 2350.45   527.7 2387.11   570.5 2408.84   584.7 2412.98   640.2 2445.53
   650.3 2454.32   696.3 2481.52   715.9 2496.31     726 2500.44   741.2 2511.39
     825 2561.05     832 2567.55   841.4 2585.53   844.3 2588.92   858.8 2597.04
#Mann= 3 ,-1 , 0
       0      .1       0   398.3    .045       0   416.4      .1       0
Bank Sta=398.3,416.4
XS Rating Curve= 0 ,0
Exp/Cntr=0.3,0.1

Type RM Length L Ch R = 1 ,3871    ,295.7,300,305.3
XS GIS Cut Line= 3
2407836.19412592686689.080125924     2407608.285      687047.725
     2407391.403      687390.414
#Sta/Elev= 30
       0 2559.69    57.4 2526.22      69  2523.3    82.7 2513.77   121.2  2492.6
   153.8 2471.03     168 2458.99     187 2454.79   202.3 2441.27   233.9 2421.56
   242.9 2412.55   258.1 2408.45   271.2 2397.31   324.4 2359.93   362.3 2335.79
     386  2327.5   402.3 2327.55   417.4 2324.73   438.1 2323.46   439.9 2324.34
     466  2348.6   518.6 2392.23   532.8 2396.52     547 2409.56     724 2536.92
   736.4 2542.09   764.8 2565.39   774.2 2576.64   809.3 2603.31   830.5 2622.38
#Mann= 3 ,-1 , 0
       0      .1       0   417.4    .045       0   439.9      .1       0
Bank Sta=417.4,439.9
XS Rating Curve= 0 ,0
Exp/Cntr=0.3,0.1

Type RM Length L Ch R = 1 ,3571    ,298.9,300,299.6
XS GIS Cut Line= 3
     2407715.981      686580.606     2407399.338      686839.438
2407078.59458528687100.045367628
#Sta/Elev= 30
       0 2545.14    22.4 2529.81    33.8 2527.64    68.8 2507.02   120.4 2471.37
   150.3 2453.79   161.6 2445.55   173.1 2443.47   182.4 2436.79   227.1 2411.58
   244.1 2398.85   256.4 2396.44   270.2 2385.89   337.4 2346.99   358.1 2333.23
   368.4 2324.83   383.4 2307.19   394.8 2304.78   401.52301.045     409 2298.49
   417.5 2300.44   425.2 2302.81   439.8 2312.99   465.2 2326.09   514.2  2356.4
   528.3 2361.07   568.2 2387.22   703.5 2480.47   760.2 2524.06   822.2 2567.13
#Mann= 3 ,-1 , 0
       0      .1       0   401.5    .045       0   417.5      .1       0
Bank Sta=401.5,417.5
XS Rating Curve= 0 ,0
Exp/Cntr=0.3,0.1

Type RM Length L Ch R = 1 ,3271    ,91.8,92.2,90.6
XS GIS Cut Line= 3
2407545.91225178 686362.13941003     2407214.794      686612.216
     2406884.585       686863.72
#Sta/Elev= 30
       0  2520.6    39.1 2499.43   105.6 2452.78   119.3 2448.49     157 2424.48
   268.4 2361.96   285.5 2346.34   299.8 2343.31   319.8 2327.19   346.4 2312.77
   384.9 2285.53   399.5 2282.81   405.5 2278.85   411.2 2277.48   431.2 2278.78
   445.4 2290.22   468.3 2294.83   482.5 2308.46   513.9 2332.51   530.7 2338.75
   544.8 2353.41   564.6 2369.77   641.3 2429.62   690.9 2464.31  741.622503.659
     767 2524.05   776.5 2537.87   782.1 2542.37   797.1 2561.11     830  2585.5
#Mann= 4 ,-1 , 0
       0      .1       0   405.5    .045       0   431.2      .1       0
  741.62      .1       0
Bank Sta=405.5,431.2
XS Rating Curve= 0 ,0
Exp/Cntr=0.5,0.3

Type RM Length L Ch R = 1 ,3178    ,216.1,215.5,214.2
XS GIS Cut Line= 3
   2407481.80769686273.878951999   2407166.71569686535.024951999
   2406842.58169686786.951951999
#Sta/Elev= 30
       0 2490.29    55.9 2459.35   196.1 2390.13   207.4 2381.05   258.6 2354.08
   279.3 2329.01   310.5 2324.53   326.7 2311.15  357.23 2293.72   383.2 2280.52
   406.3 2279.14  415.612274.793   420.5 2270.82   429.5 2268.23   437.6 2270.58
   449.7  2282.5   464.9 2287.78   487.2 2307.24   503.2  2312.6   519.8  2326.6
   535.9 2333.36     546 2342.42   558.9 2359.43   600.1 2393.77   651.4 2435.24
  697.652466.469   791.1 2538.29  810.822564.994  817.722569.262   819.8 2570.47
#Mann= 8 ,-1 , 0
       0      .1       0  357.23     .06       0  415.61      .1       0
   420.5    .045       0   437.6      .1       0  697.65      .1       0
  810.82      .1       0  817.72      .1       0
#XS Ineff= 2 , 0
             412    2322   443.3            2323
Permanent Ineff=
       F       F
Bank Sta=420.5,437.6
XS Rating Curve= 0 ,0
Exp/Cntr=0.5,0.3

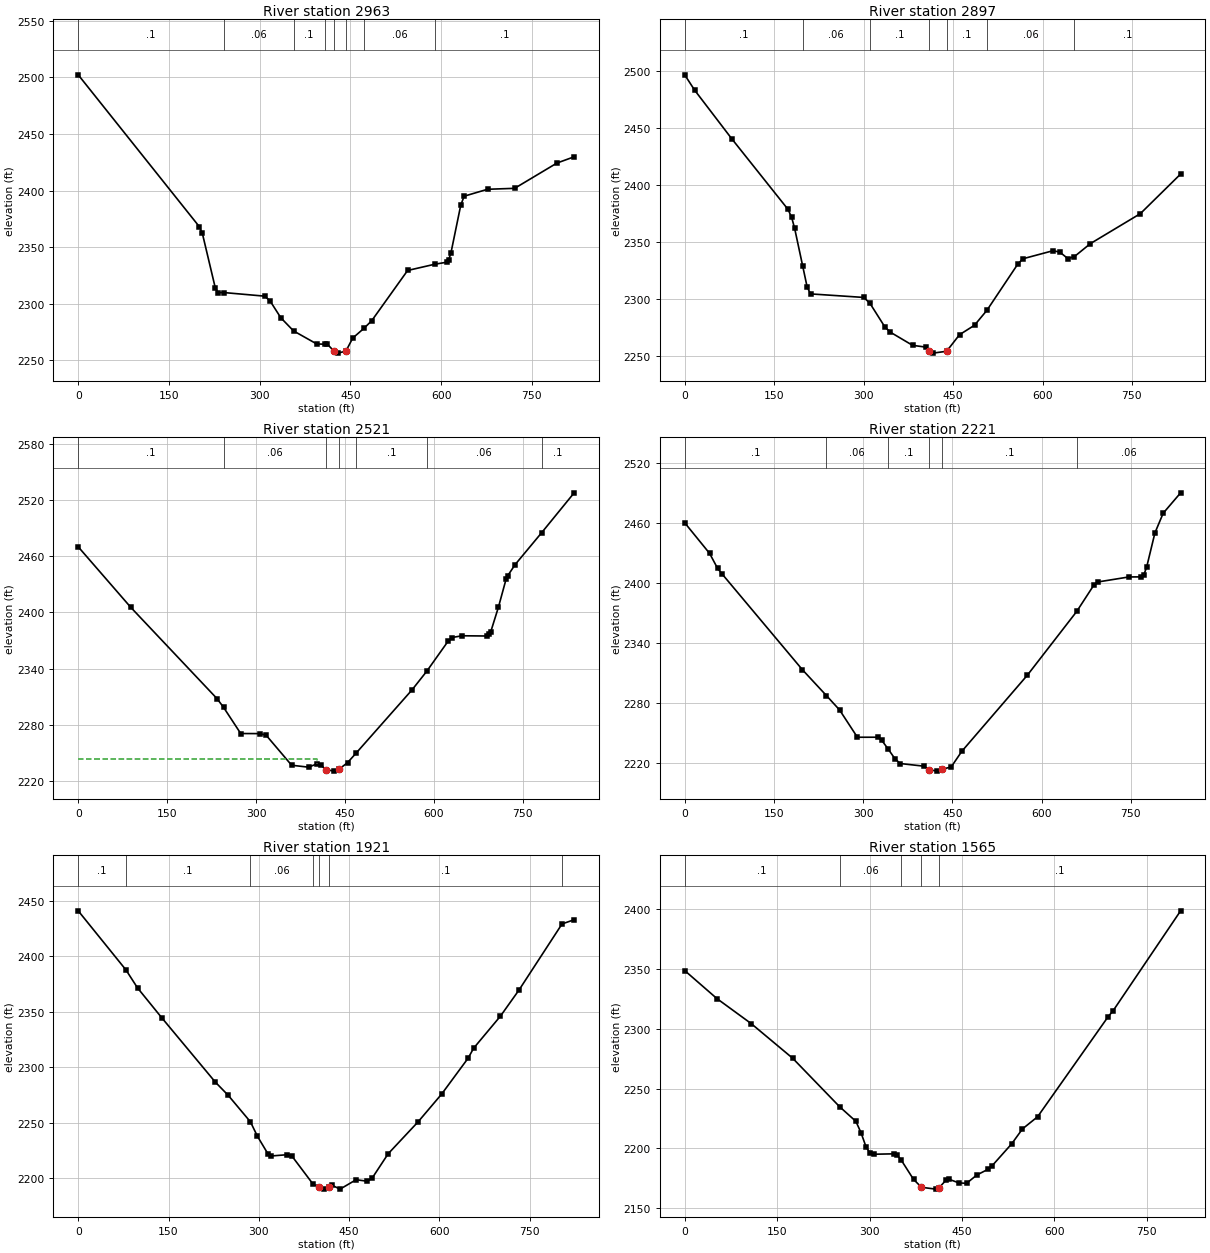
Type RM Length L Ch R = 1 ,2963    ,64.8,66.2,66.5
XS GIS Cut Line= 3
2407353.62598894686103.0129130672407035.73398894686362.732913067
2406728.98398894686633.748913067
#Sta/Elev= 30
       0 2502.32     200 2368.18   205.2 2362.14   226.5 2314.11     231 2309.78
   241.22309.756   308.5 2306.58   317.5 2302.08   334.9 2287.48  355.922275.866
   394.3 2264.31  407.282264.111   411.8  2264.1   422.8 2257.99   428.9 2256.21
   442.5 2257.96   453.8 2269.53  472.07 2278.02     485 2284.76   544.5  2329.3
   589.52334.835   609.7 2336.66   612.5 2338.88   616.1 2344.74   632.4  2387.2
     638 2394.99   676.6 2401.11   721.4 2401.94   791.3 2424.29   819.8 2429.83
#Mann= 8 ,-1 , 0
       0      .1       0   241.2     .06       0  355.92      .1       0
  407.28     .06       0   422.8    .045       0   442.5     .06       0
  472.07     .06       0   589.5      .1       0
Bank Sta=422.8,442.5
XS Rating Curve= 0 ,0
Exp/Cntr=0.5,0.3

Type RM Length L Ch R = 1 ,2897    ,375.3,376.1,376.4
XS GIS Cut Line= 3
 2407313.2887123686069.686338191 2406981.2627123 686323.41733819
2406662.71077702686587.485683497
#Sta/Elev= 30
       0 2496.35    16.9 2482.78    78.7 2440.53   173.3 2378.52   179.4 2371.46
   184.4 2361.87  197.75 2329.27   205.3  2310.7     211 2304.54   300.2 2301.44
  310.422296.486   335.5 2275.75   344.5 2271.13   382.2 2259.49     405 2257.91
   410.4 2254.25   416.4 2252.68   439.2 2254.31   460.9 2268.82     486  2277.1
  506.842290.199   558.5 2330.58     567 2335.28   617.6 2342.34     629 2341.15
   642.7 2335.38  653.612337.263   680.3 2348.56   764.1 2374.82   831.6 2409.48
#Mann= 7 ,-1 , 0
       0      .1       0  197.75     .06       0  310.42      .1       0
   410.4    .045       0   439.2      .1       0  506.84     .06       0
  653.61      .1       0
Bank Sta=410.4,439.2
XS Rating Curve= 0 ,0
Exp/Cntr=0.3,0.1

Type RM Length L Ch R = 1 ,2521    ,295.6,300,301.7
XS GIS Cut Line= 3
2407109.67775873685774.991956004     2406761.879      686026.377
     2406445.483      686283.365
#Sta/Elev= 30
       0 2469.98    88.6 2405.47   234.1 2308.12  245.172298.837   274.2 2270.83
   307.1 2270.74   317.2 2268.94   360.1 2237.01   388.6 2234.95   403.4 2238.62
   409.5 2237.31   417.4 2232.42   431.7 2230.73   440.3 2232.87   454.5 2239.81
  468.592249.717   563.2 2317.35  588.282337.406   623.8 2369.04   630.8 2373.24
   647.8 2375.09   690.1 2374.84   693.3 2376.46   696.2 2379.61   709.1 2405.75
   721.8 2435.16   724.6 2439.03   737.2    2451   781.92484.986   836.8 2527.55
#Mann= 7 ,-1 , 0
       0      .1       0  245.17     .06       0   417.4    .045       0
   440.3     .06       0  468.59      .1       0  588.28     .06       0
   781.9      .1       0
#XS Ineff= 2 , 0
          402.77 2243.68
Permanent Ineff=
       F       F
Bank Sta=417.4,440.3
XS Rating Curve= 0 ,0
Exp/Cntr=0.3,0.1

Type RM Length L Ch R = 1 ,2221    ,298,300,300.7
XS GIS Cut Line= 3
     2406988.337      685592.135     2406606.121      685779.313
     2406253.352      685984.383
#Sta/Elev= 30
       0 2460.37    41.9  2429.7    55.2 2414.86      63 2409.05   197.7 2313.48
  238.192287.544   260.4  2273.1   290.3 2245.84   324.6 2245.85   331.4 2242.65
  341.98 2234.06   353.6 2224.17   362.5 2219.53   402.6 2216.88   409.9 2213.37
   424.6 2211.95   433.12213.859     448 2216.16   465.8 2231.75     576 2307.91
  658.982371.669   687.4 2397.69     694 2401.09   746.7 2406.16   767.2 2406.22
   771.9 2408.52   776.5 2415.98   790.4 2450.21   804.3  2469.9   833.6 2490.29
#Mann= 6 ,-1 , 0
       0      .1       0  238.19     .06       0  341.98      .1       0
   409.9    .045       0   433.1      .1       0  658.98     .06       0
Bank Sta=409.9,433.1
XS Rating Curve= 0 ,0
Exp/Cntr=0.3,0.1

Type RM Length L Ch R = 1 ,1921    ,353.3,356,356.6
XS GIS Cut Line= 3
     2406891.977      685324.967     2406522.105      685499.574
     2406148.309      685679.161
#Sta/Elev= 30
       0 2441.24   79.352387.812    98.5 2371.62   138.5  2344.8   227.7 2286.52
   249.1 2274.57  286.052250.595   297.7 2237.53   315.4 2221.42   319.8 2219.73
   346.4 2220.87   355.2  2219.5   389.42194.779   399.5 2191.47     408 2189.84
   416.5 2191.89   421.6 2193.29   434.9 2189.81   461.6 2198.31     480 2196.96
   488.2 2199.75   514.8 2221.77   564.5 2250.61   603.6 2275.66   647.6 2308.13
   656.8 2317.16   701.2 2346.05   732.3 2369.84  803.592429.409   823.7 2433.19
#Mann= 7 ,-1 , 0
       0      .1       0   79.35      .1       0  286.05     .06       0
   389.4      .1       0   399.5    .045       0   416.5      .1       0
  803.59     .06       0
Bank Sta=399.5,416.5
XS Rating Curve= 0 ,0
Exp/Cntr=0.3,0.1

Type RM Length L Ch R = 1 ,1565    ,272.8,275.6,276.1
XS GIS Cut Line= 2
2406820.91632445685046.9358094582406049.87798782685277.377718338
#Sta/Elev= 30
       0 2348.81    52.4  2325.3   107.8 2304.45   175.3 2275.37  251.352234.853
   277.8 2222.58   286.2 2212.96   294.5 2200.85   300.6 2196.29     307 2195.06
   340.4  2195.4   344.6 2194.44  351.512190.042   371.3 2174.04   384.2  2167.4
   407.2 2165.85   413.1 2167.21   423.9 2173.29   428.1 2174.26   444.8 2171.09
   457.3 2170.67     474 2177.66   491.6 2182.29   499.1 2185.55   530.7 2203.83
   548.1 2216.26   572.6 2226.41   686.9 2310.03   695.3 2315.27   804.7 2398.79
#Mann= 5 ,-1 , 0
       0      .1       0  251.35     .06       0  351.51      .1       0
   384.2    .045       0   413.1      .1       0
Bank Sta=384.2,413.1
XS Rating Curve= 0 ,0
Exp/Cntr(USF)=0,0
Exp/Cntr=0.3,0.1

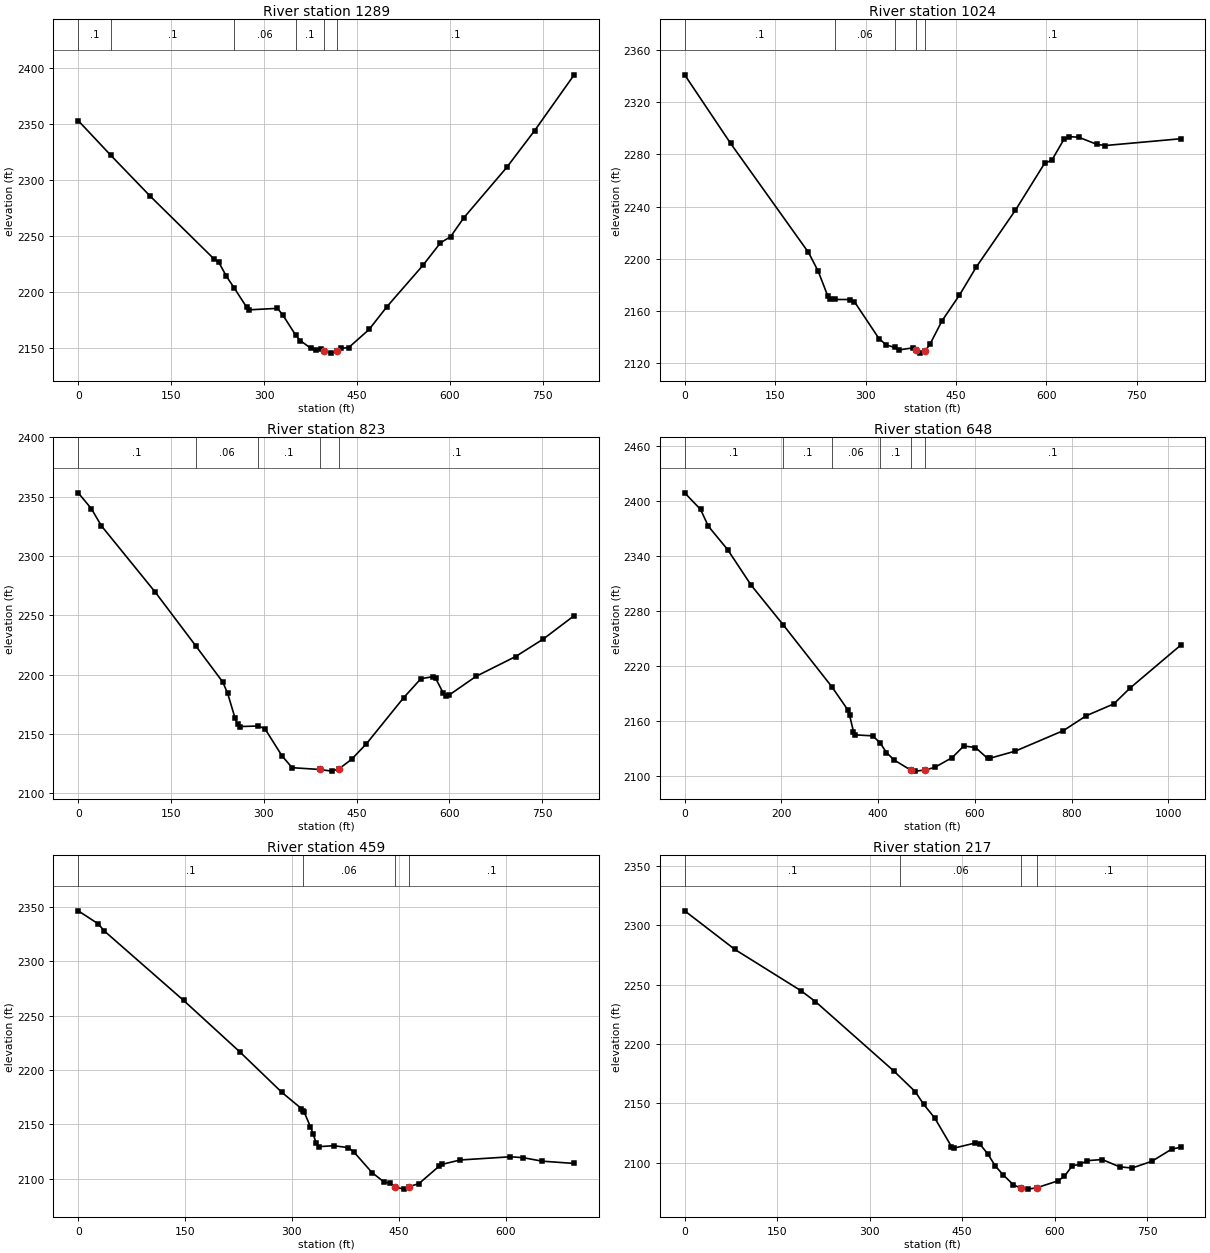
Type RM Length L Ch R = 1 ,1289    ,263.6,265.6,266.9
XS GIS Cut Line= 2
2406783.52339924684806.4273290682406004.77010462684991.267605222
#Sta/Elev= 30
       0 2352.66   52.322321.822   115.9 2285.35   218.7 2229.37     227 2226.07
   239.2 2213.58  251.482203.468   272.1  2185.8   276.2  2183.7   321.5    2185
     330 2179.27  351.052160.995   358.5 2156.11   374.9 2149.62   383.1    2148
   391.4  2148.9   396.4 2147.01   407.8 2145.02  417.32 2146.91   424.2 2149.32
   436.6    2150   469.5 2166.18   498.2 2186.49   556.3  2223.4   584.6  2243.5
     601 2249.03   622.3 2265.87   691.5 2310.83   736.7 2343.81   800.4 2393.55
#Mann= 6 ,-1 , 0
       0      .1       0   52.32      .1       0  251.48     .06       0
  351.05      .1       0   396.4    .045       0  417.32      .1       0
Bank Sta=396.4,417.32
XS Rating Curve= 0 ,0
Exp/Cntr(USF)=0,0
Exp/Cntr=0.3,0.1

Type RM Length L Ch R = 1 ,1024    ,198,200.8,201.4
XS GIS Cut Line= 2
2406746.19159308684589.8258836862405931.07324676684699.171027705
#Sta/Elev= 30
       0 2341.04    76.1 2288.53   205.3 2204.89   221.4 2190.55   237.6 2171.15
   241.6 2168.99  248.732168.861   273.9 2168.83   281.6 2167.06   322.3 2138.83
   334.4 2134.02  348.082132.123   354.6 2130.16   378.8 2131.82   382.8 2130.15
   390.9 2127.75   399.1 2129.54   407.1 2134.88   426.9 2152.64   455.5 2172.08
   483.7 2193.84   548.5  2237.3   596.7 2273.09     609 2275.72     629 2291.66
   637.1 2293.64   653.2 2293.26   683.7 2287.72   697.3 2286.85822.4198 2292.04
#Mann= 5 ,-1 , 0
       0      .1       0  248.73     .06       0  348.08      .1       0
   382.8    .045       0   399.1      .1       0
Bank Sta=382.8,399.1
XS Rating Curve= 0 ,0
Exp/Cntr(USF)=0,0
Exp/Cntr=0.3,0.1

Type RM Length L Ch R = 1 ,823     ,172.7,174.6,173.1
XS GIS Cut Line= 3
2406760.04487682  684428.07609192406165.82360235684455.613175352
2406045.53002728684623.734316421
#Sta/Elev= 30
       0 2353.28    21.3 2339.88    37.3 2325.56   124.4 2269.56  190.122224.076
   233.6 2193.69   241.6 2184.01   253.6 2162.98   257.6 2158.11   261.6 2156.09
  290.092156.542   301.6 2154.42   329.2  2131.5   345.7 2121.38   390.5 2119.87
   409.6 2118.48   421.1 2120.24   441.8 2128.43   465.8 2141.53   525.9 2180.34
   553.9 2196.47   573.9  2198.2   577.9 2196.63   589.9 2184.48   594.9 2181.75
   598.9 2182.46   643.2 2198.49   707.1 2215.18   751.4 2229.81   801.6 2249.62
#Mann= 5 ,-1 , 0
       0      .1       0  190.12     .06       0  290.09      .1       0
   390.5    .045       0   421.1      .1       0
Bank Sta=390.5,421.1
XS Rating Curve= 0 ,0
Exp/Cntr(USF)=0,0
Exp/Cntr=0.3,0.1

Type RM Length L Ch R = 1 ,648     ,193,189.6,185.1
XS GIS Cut Line= 3
2406847.58436299684261.7904516292406221.80091091684282.146938878
2406008.60889433684619.647286601
#Sta/Elev= 30
       0  2409.1    32.9 2390.94    48.9  2372.7    88.9 2347.06   137.5 2308.28
  204.262264.688   304.42197.392     337 2172.48     341 2166.28     349 2148.54
     353    2145     389 2143.94  404.54  2135.9   417.1 2125.78   433.1 2117.55
     467 2106.69   477.1 2105.46   497.1 2106.67   516.8 2109.51   553.1 2120.23
   577.1 2132.91   601.2 2131.22   626.1 2119.42   631.8 2119.62   683.8 2127.34
   783.1 2149.71   830.4 2165.95   887.2 2178.81   920.3 2195.87 1025.31  2242.8
#Mann= 6 ,-1 , 0
       0      .1       0  204.26      .1       0   304.4     .06       0
  404.54      .1       0     467    .045       0   497.1      .1       0
Bank Sta=467,497.1
XS Rating Curve= 0 ,0
Exp/Cntr(USF)=0,0
Exp/Cntr=0.3,0.1

Type RM Length L Ch R = 1 ,459     ,242.4,241.6,242.3
XS GIS Cut Line= 4
2406814.00496668684124.4231565392406530.35561555684050.514522793
2406300.63959174684108.4429114042406220.73836607684254.262648253
#Sta/Elev= 30
       0 2346.46    28.2 2334.43    36.4 2328.05     148 2263.99   226.6 2216.83
   285.9 2179.41   313.3  2164.5   316.2 2162.06   317.5 2160.89   326.1 2147.55
   329.8 2141.38     334 2132.68   338.1 2129.43   358.7  2130.3   379.3 2128.53
   387.6 2124.12   412.4 2105.63   428.9 2097.12   438.1 2095.58   444.42092.251
   457.6 2090.34   464.4 2092.57   478.4 2095.43   507.2 2111.73   511.4 2113.22
   536.2 2117.16   606.9 2120.11   624.6 2119.29   651.4 2116.07   696.3 2113.97
#Mann= 4 ,-1 , 0
       0      .1       0   316.2     .06       0   444.4    .045       0
   464.4      .1       0
Bank Sta=444.4,464.4
XS Rating Curve= 0 ,0
Exp/Cntr(USF)=0,0
Exp/Cntr=0.3,0.1

Type RM Length L Ch R = 1 ,217     ,201.2,201.2,201.2
XS GIS Cut Line= 4
2406877.72558606684030.0222165612406488.09034843683825.330379348
2406306.26153709 683874.818866272406286.30892404684049.223426144
#Sta/Elev= 30
       0 2312.24    81.5 2279.67   188.2 2245.06   211.9 2235.83   339.3 2177.21
   373.9 2159.87   387.4 2149.31   405.5 2137.67   432.6 2113.64   437.1  2112.4
   470.5 2116.59   478.8 2115.59   491.3 2107.58   503.7 2097.27   516.1 2089.97
   532.7 2081.59   545.2 2078.55   556.5 2077.81   570.8 2078.92   605.4 2084.83
   615.6 2088.53   628.6  2097.6   640.7 2098.64   652.8 2101.81     677 2102.73
   705.1  2096.6   725.3 2095.58   757.5 2101.26   789.7 2111.53   804.1 2113.08
#Mann= 4 ,-1 , 0
       0      .1       0  349.86     .06       0   545.2    .045       0
   570.8      .1       0
Bank Sta=545.2,570.8
XS Rating Curve= 0 ,0
Exp/Cntr(USF)=0,0
Exp/Cntr=0.3,0.1

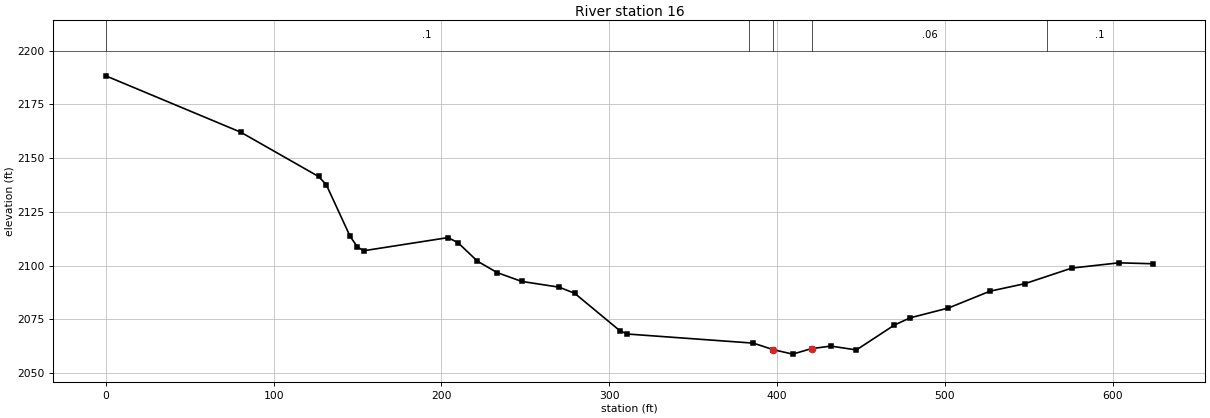
Type RM Length L Ch R = 1 ,16      ,,,
XS GIS Cut Line= 4
2406676.34819337683808.1005503832406362.04615098683625.310780021
2406306.14826385683684.8359898092406291.34208396683863.062423571
#Sta/Elev= 30
       0 2188.31    80.5 2162.04   126.8 2141.44   131.4 2137.63   145.6 2113.58
   149.9  2108.7   153.6 2106.86   203.9 2112.98   209.8 2110.69   221.5 2102.01
   233.2 2096.71   247.8  2092.6   270.2 2089.91   279.5 2087.02   306.3 2069.67
   310.7 2068.11   385.9 2063.86   397.6 2060.86   409.3 2058.74   420.6 2061.31
   432.1 2062.48   447.3 2060.69     470  2072.3   479.4 2075.65   502.2 2080.22
   526.9 2088.04   547.7 2091.54   575.7  2098.8   603.8 2101.25   624.1 2100.81
#Mann= 5 ,-1 , 0
       0      .1       0  383.05     .06       0   397.6    .045       0
   420.6     .06       0  561.14      .1       0
Bank Sta=397.6,420.6
XS Rating Curve= 0 ,0
Exp/Cntr(USF)=0,0
Exp/Cntr=0.3,0.1
LCMann Table=0

Chan Stop Cuts=-1
Use User Specified Reach Order=0
Composite Channel Slope=5